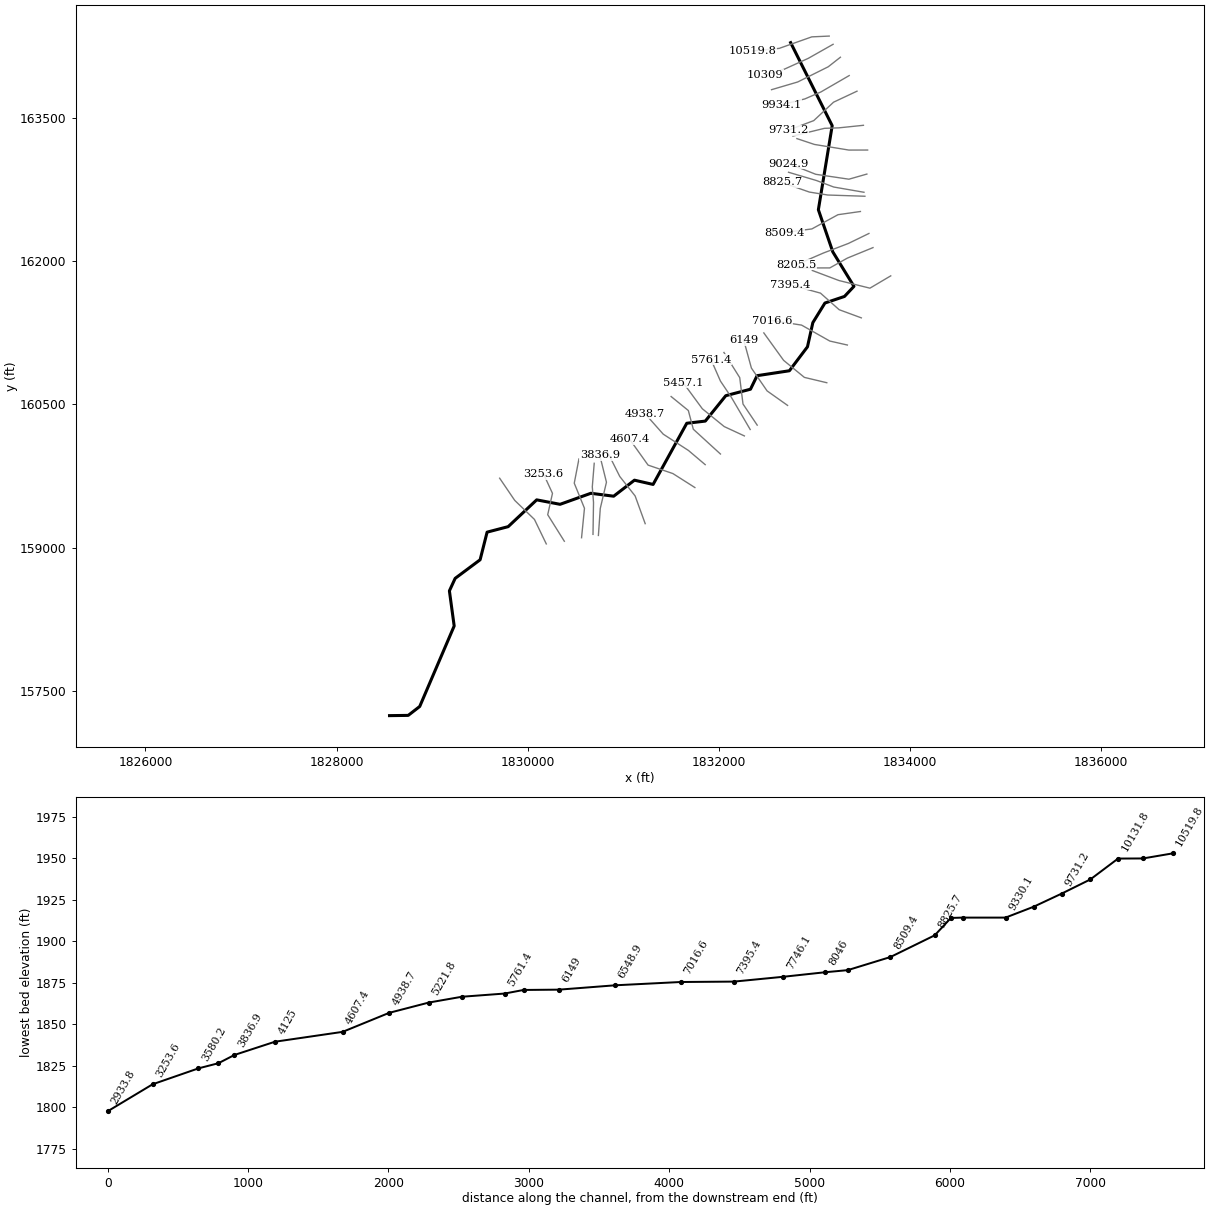
--- Bottom Creek.prj (project) ---

Proj Title=Bottom Creek
Current Plan=p01
Default Exp/Contr=0,0
English Units
Geom File=g01
Flow File=f01
Plan File=p01
BEGIN DESCRIPTION:
END DESCRIPTION:
DSS Export Rating Curves= 0
DSS Export Rating Curve Sorted= 0
DSS Export Volume Flow Curves= 0
DXF OffsetX= 0
DXF OffsetY= 0
DXF ScaleX= 0
DXF ScaleY= 0

--- Bottom Creek.p01 (plan) ---

Plan Title=Floodplain
Program Version=4.00
Geom File=g01
Flow File=f01
K Sum by GR=0
Std Step Tol=0.01
Critical Tol=0.01
Num of Std Step Trials=20
Max Error Tol=0.3
Flow Tol Ratio=0.001
Split Flow NTrial=30
Split Flow Tol=0.02
Split Flow Ratio=0.02
Log Output Level=0
Friction Slope Method=1
Unsteady Friction Slope Method=2
Unsteady Bridges Friction Slope Method=1
Global Log Level=0
CheckData=False
Run HTab=0
Run UNet=0
Run PostProcess=0
UNET Theta=0
UNET Theta Warmup=0
UNET ZTol=0
UNET ZSATol=0
UNET MxIter=0
UNET MaxInSteps=0
UNET DtIC=0
UNET DtMin=0
UNET MaxCRTS=0
UNET WFStab=0
UNET SFStab=0
UNET WFX=0
UNET SFX=0
UNET DSS MLevel=0
UNET DZMax Abort=0
UNET Convert EG Bridges=0
UNET Use Existing IB Tables=0
UNET Froude Limit=0
UNET Froude Power=0
Write IC File=0
Echo Input=False
Echo Output=False
Write Detailed=0

--- Bottom Creek.f01 (steady flow) ---

Flow Title=NFF Regression Equation
Program Version=4.00
Number of Profiles=1
Profile Names=P100yr
River Rch & RM=Bottom Creek,Main      ,10519.8
590.6027
River Rch & RM=Bottom Creek,Main      ,9530.4
649.6669
River Rch & RM=Bottom Creek,Main      ,8046
695.8246
River Rch & RM=Bottom Creek,Main      ,7746.1
1147.688
River Rch & RM=Bottom Creek,Main      ,4125
1273.101
River Rch & RM=Bottom Creek,Main      ,322.9
1405.827
Boundary for River Rch & Prof#=Bottom Creek,Main      ,1
Up Type=0
Dn Type=3
Dn Slope=0.038585

--- Bottom Creek.g01 (geometry) ---

Geom Title=USGS 10m DEM
Program Version=4.00

River Reach=Bottom Creek    ,Main
Reach XY= 30
     1832753.071      164286.592     1833187.945      163417.314
     1833043.233      162537.461     1833194.414      162096.365
     1833415.651        161735.4     1833316.676      161629.957
     1833112.094       161561.15     1832985.439      161355.942
     1832929.189      161102.742     1832739.942      160852.079
     1832401.974      160800.644     1832332.757      160658.975
     1832074.001      160591.052     1831859.881       160325.18
     1831665.813      160302.539     1831313.258      159662.117
     1831118.167      159706.667     1830900.512      159538.973
      1830661.84      159569.612     1830339.568      159454.069
     1830094.762      159500.699     1829796.301      159220.292
     1829575.712      159162.718     1829502.613      158873.559
      1829241.27      158678.845     1829181.109      158548.173
     1829231.141      158180.494     1828870.401      157337.971
     1828749.894      157244.696     1828554.273      157242.102

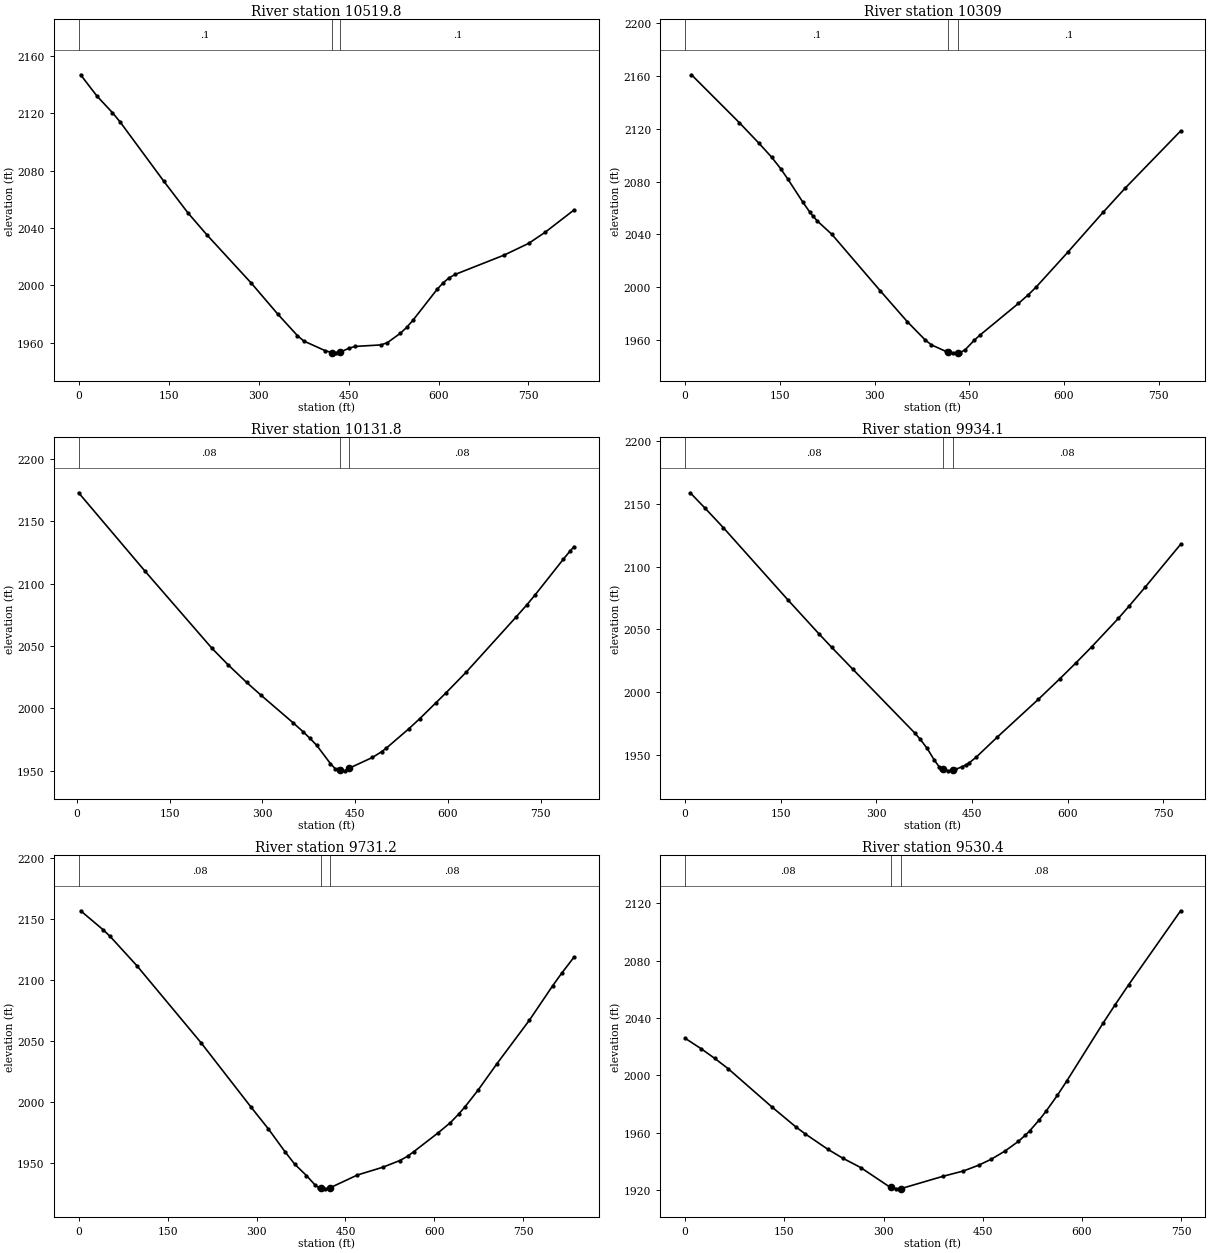
Type RM Length L Ch R = 1 ,10519.8 ,209,210.7,212.4
XS GIS Cut Line= 4
     1833156.859      164355.328     1832974.692      164347.136
     1832633.802       164226.73     1832352.852      164199.329
#Sta/Elev= 30
     3.3 2146.93    30.5 2132.12    56.3 2120.54      69 2114.13   141.5 2072.98
   182.3 2050.59   214.5    2035   287.9 2001.62   332.5 1979.81   364.7 1965.07
   375.4 1961.25   411.4 1954.47   421.6 1953.25   429.1 1953.02   436.6  1953.6
   450.5  1956.2   461.3  1957.5   504.2 1958.55   514.9 1960.16   536.3 1966.63
   546.9 1970.76   557.1 1975.59   597.7 1997.31   607.9 2001.91     618 2005.43
   628.2 2007.77   709.5  2021.2   750.2 2029.33     778 2037.16   826.2 2052.74
#Mann= 3 , 0 , 0
       0      .1       0   421.6    .045       0   436.6      .1       0
Bank Sta=421.6,436.6
XS Rating Curve= 0 ,0
Exp/Cntr=0.3,0.1

Type RM Length L Ch R = 1 ,10309   ,176.5,177.2,177.9
XS GIS Cut Line= 4
     1833197.376      164269.243     1832938.385      164122.645
     1832679.394      164005.366     1832483.929      163951.613
#Sta/Elev= 30
    10.1 2161.02    86.1 2124.57   116.6 2109.24   136.9 2098.55   151.3 2089.79
   162.9 2081.69   186.1 2064.58   197.8 2056.56   201.9  2054.1   209.3 2050.08
   232.6  2039.8     309 1997.08   351.9  1973.6   379.9 1959.86   390.1    1956
   412.8 1951.11   416.8  1950.6   424.3 1949.98   431.8 1950.15   435.4  1950.2
   443.6 1952.38   457.6 1959.41   466.6 1963.32   527.7 1987.46     543 1993.87
   555.6 1999.79   605.8 2026.29   662.1 2056.78   696.3 2074.75   784.6 2118.39
#Mann= 3 , 0 , 0
       0      .1       0   416.8    .045       0   431.8      .1       0
Bank Sta=416.8,431.8
XS Rating Curve= 0 ,0
Exp/Cntr=0.3,0.1

Type RM Length L Ch R = 1 ,10131.8 ,198.8,197.8,196.7
XS GIS Cut Line= 4
     1833273.831      164133.793     1833146.627      164033.946
     1832826.705      163874.801     1832553.054      163794.172
#Sta/Elev= 30
     2.7 2172.83   110.2 2109.93   218.2 2048.25   244.1 2035.11   274.6 2020.75
   297.2 2010.78   349.8 1988.37   365.6 1981.35   376.3 1976.26   387.6  1970.5
   410.1 1955.65   417.7 1951.65   421.5 1951.03   425.1 1950.98  433.02 1949.91
   440.1 1951.96     478 1960.65   493.1 1965.35   500.6 1968.18   536.6 1983.53
   554.6 1991.78   580.6 2004.43   597.1 2012.49   629.5 2028.96   709.9 2072.99
   727.3 2082.75   740.8 2090.77   786.5  2119.4   797.1 2125.79   804.3 2129.75
#Mann= 3 , 0 , 0
     2.7     .08       0   425.1    .045       0   440.1     .08       0
Bank Sta=425.1,440.1
XS Rating Curve= 0 ,0
Exp/Cntr=0.3,0.1

Type RM Length L Ch R = 1 ,9934.1  ,196.1,202.9,209.7
XS GIS Cut Line= 4
     1833365.964       163941.84     1833070.324      163770.808
     1832901.735      163697.508     1832657.404      163636.426
#Sta/Elev= 30
       8 2158.75    31.3 2146.51    59.8 2131.07     161  2073.6     210 2046.39
     230 2035.63   262.8 2018.38   359.8 1967.68   368.6 1962.57   379.6 1955.26
   390.7 1945.99   398.2 1940.77   401.7 1939.15   405.2 1938.63   412.7 1937.33
   420.2 1937.93   423.8 1938.41   434.8 1940.68   440.9 1942.32   445.8 1943.75
   456.8 1948.33   489.9 1964.32   554.2 1994.36   587.6 2010.56   612.6 2023.09
   637.6 2036.03   679.6 2058.77     696  2068.3   721.3 2083.44   777.2 2117.74
#Mann= 3 , 0 , 0
       0     .08       0   405.2    .045       0   420.2     .08       0
Bank Sta=405.2,420.2
XS Rating Curve= 0 ,0
Exp/Cntr=0.3,0.1

Type RM Length L Ch R = 1 ,9731.2  ,215.3,200.8,186.4
XS GIS Cut Line= 4
     1833447.673      163778.593     1833202.262      163663.302
     1832994.581       163470.28     1832731.683      163371.374
#Sta/Elev= 30
     3.4 2157.03    41.4 2141.41    53.2 2135.95    97.9 2112.12   206.6 2048.63
   291.1 1995.66     320 1978.02   348.3  1959.1   364.5 1949.02   384.1 1939.77
   398.4 1932.17   405.6 1929.63   408.6 1929.28   416.1 1928.84   423.6 1929.61
     470 1940.18   512.8 1946.55   541.6 1952.06   554.7 1955.58   565.1 1959.33
   605.3 1974.45   626.7 1983.08   640.8 1990.17   651.6 1996.22   673.2 2009.61
   705.6 2031.69   760.2 2067.31   799.4 2095.54   815.1 2106.17   835.6 2119.13
#Mann= 3 , 0 , 0
       0     .08       0   408.6    .045       0   423.6     .08       0
Bank Sta=408.6,423.6
XS Rating Curve= 0 ,0
Exp/Cntr=0.3,0.1

Type RM Length L Ch R = 1 ,9530.4  ,204.2,200.3,196.3
XS GIS Cut Line= 4
     1833515.006      163421.414     1833256.015      163394.538
     1833106.973      163389.651     1832777.126      163309.022
#Sta/Elev= 30
      .5 2025.69    24.6 2018.43    44.9 2011.76    65.2 2004.58   131.5 1977.84
   166.9 1964.24     182 1959.04   216.1 1948.36   238.1  1942.3   265.5  1935.7
   309.1 1922.24   311.7 1921.86   319.2 1920.88   326.7 1921.07     390 1929.64
   420.7 1933.32   443.8 1937.36   462.4 1941.42   483.2 1947.09   503.8 1953.95
   514.4 1958.31   520.9 1961.29   535.3 1968.86   545.7 1975.01   562.7 1986.02
   576.9 1995.99   632.4 2036.77   649.8 2048.99   670.6 2063.17   749.1 2114.67
#Mann= 3 , 0 , 0
       0     .08       0   311.7    .045       0   326.7     .08       0
Bank Sta=311.7,326.7
XS Rating Curve= 0 ,0
Exp/Cntr=0.3,0.1

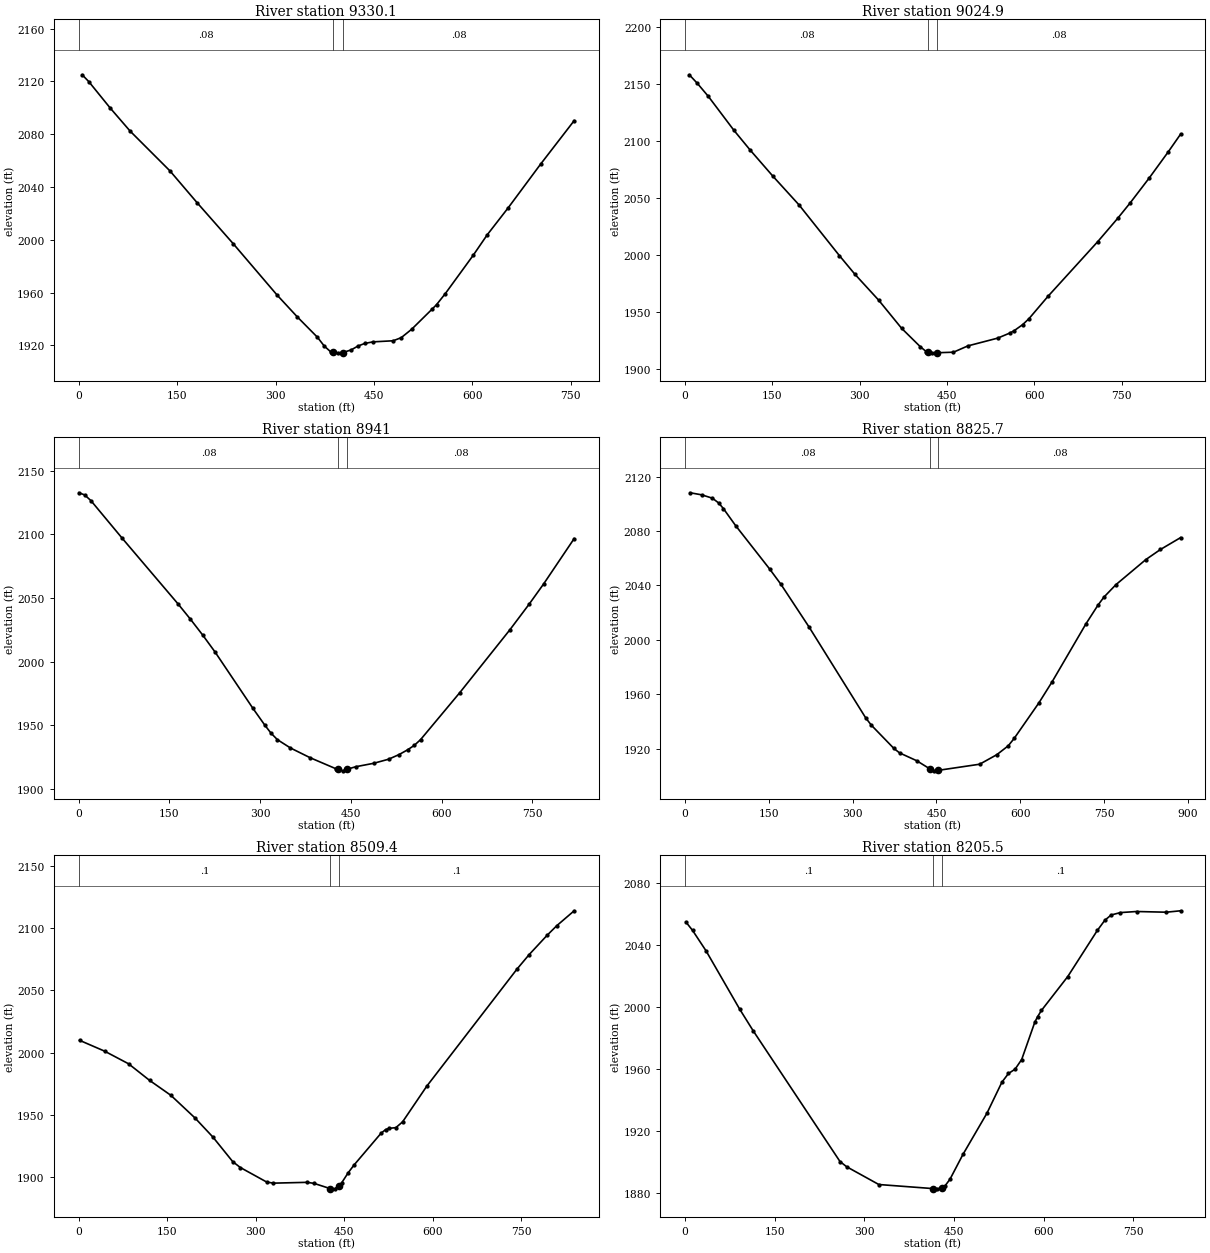
Type RM Length L Ch R = 1 ,9330.1  ,304.9,305.2,305.5
XS GIS Cut Line= 4
     1833558.986      163162.423     1833362.649      163162.137
     1833001.911      163221.062     1832818.663      163282.145
#Sta/Elev= 30
     5.4 2124.97    15.5 2119.78    48.2 2099.72    78.5 2082.28   139.2 2052.13
   180.5 2028.06   235.4 1997.08   302.4 1958.08   333.2 1941.54   363.9  1926.1
   374.2  1919.5   384.4 1914.92   387.2 1914.77   394.7 1914.33   402.2 1914.48
   415.2 1916.55   425.4 1919.42   435.7 1921.42   448.4 1922.64   479.2 1923.47
   491.5 1925.83   507.4 1932.19   538.2 1947.27   545.3 1950.82   558.7 1959.22
   601.2 1988.25   622.5 2003.72   654.5 2024.21   703.7 2057.18     755 2090.23
#Mann= 3 , 0 , 0
       0     .08       0   387.2    .045       0   402.2     .08       0
Bank Sta=387.2,402.2
XS Rating Curve= 0 ,0
Exp/Cntr=0.3,0.1

Type RM Length L Ch R = 1 ,9024.9  ,88.2,83.9,79.5
XS GIS Cut Line= 4
     1833551.036      162910.944     1833362.901      162857.191
     1833015.951      162908.501     1832732.527      163020.893
#Sta/Elev= 30
     7.2 2158.21    20.8 2150.83      40 2139.21    83.9 2109.48   111.5 2092.36
   151.2 2069.05   195.7 2044.09     265 1999.65   291.7 1983.27   332.5 1960.55
   371.9 1935.88     404 1919.73   414.3 1915.42     417 1915.15   424.5 1914.33
     432 1914.39     461 1914.89   485.8 1920.42     537 1927.23   558.1 1931.74
   565.2 1933.73   579.9 1939.06   590.8 1944.32   623.4 1963.88     709 2011.92
   743.1 2032.26   764.9 2046.02   797.5 2067.79   830.3 2090.81   851.3 2106.18
#Mann= 3 , 0 , 0
       0     .08       0     417    .045       0     432     .08       0
Bank Sta=417,432
XS Rating Curve= 0 ,0
Exp/Cntr=0.3,0.1

Type RM Length L Ch R = 1 ,8941    ,111.3,115.3,119.4
XS GIS Cut Line= 4
     1833520.642      162720.422     1833204.578      162775.151
     1833022.602      162843.563     1832731.167      162929.763
#Sta/Elev= 30
      .5 2132.53      10 2130.85    20.3 2126.37    71.6 2097.05     164 2045.42
   184.5 2033.41     205 2020.83   225.6  2007.4   287.9 1963.34   307.7 1950.05
     318 1943.72   328.6 1938.61   350.2 1932.07   382.6 1924.45   425.9 1915.65
   429.2  1915.4   436.7 1914.13   444.2 1915.44   458.3 1917.38   487.6 1920.04
   512.3 1923.25   529.9 1926.96   543.6  1930.6   554.6 1934.05   565.1 1938.59
   630.1 1975.59   712.8  2024.9   744.5 2044.94   768.7 2060.99   819.1 2096.56
#Mann= 3 , 0 , 0
       0     .08       0   429.2    .045       0   444.2     .08       0
Bank Sta=429.2,444.2
XS Rating Curve= 0 ,0
Exp/Cntr=0.3,0.1

Type RM Length L Ch R = 1 ,8825.7  ,303.1,316.3,329.5
XS GIS Cut Line= 4
     1833530.492      162678.768     1833142.113      162691.531
     1832948.835      162722.529     1832662.566      162822.814
#Sta/Elev= 30
     9.2 2108.14    29.8 2106.62    48.9 2104.16    60.2 2100.61    68.5 2096.56
    90.5 2083.97   151.3 2052.12   171.5 2040.88   222.1 2009.33   323.3 1942.63
   333.4 1937.25   373.9  1920.1     384 1916.85   414.7 1911.09     438 1905.16
   445.5 1903.66     453 1904.01   527.4 1908.53   558.1 1915.54   578.6 1922.08
   589.1 1927.48   633.3 1953.56   657.1 1969.14   717.7 2011.79   739.1 2025.45
   749.8 2031.39   771.3 2040.55   824.9 2059.02   851.1 2066.45   887.2 2075.19
#Mann= 3 , 0 , 0
       0     .08       0     438    .045       0     453     .08       0
Bank Sta=438,453
XS Rating Curve= 0 ,0
Exp/Cntr=0.3,0.1

Type RM Length L Ch R = 1 ,8509.4  ,306.7,303.9,301.1
XS GIS Cut Line= 4
     1833483.417      162519.113     1833248.685      162485.626
     1832975.035      162336.584     1832686.399      162298.754
#Sta/Elev= 30
     1.5  2009.8    43.9 2001.11    84.6 1990.95   120.4 1977.56   156.3 1965.63
   197.1  1947.5   227.7 1932.04   261.1 1912.42     274 1907.68   318.7 1896.01
   330.2 1895.12   387.8 1895.78   399.4 1894.86   426.4 1890.73   433.9 1890.55
   441.4 1893.17   445.6 1895.25   456.9  1903.5   466.7 1909.66   512.6 1935.24
   520.1 1938.05   526.1 1939.12   537.6 1939.67     549 1944.32   589.9  1972.9
   742.9 2066.97   763.3 2078.49   793.9 2094.09   810.4 2101.84   839.8 2113.78
#Mann= 3 , 0 , 0
       0      .1       0   426.4    .045       0   441.4      .1       0
Bank Sta=426.4,441.4
XS Rating Curve= 0 ,0
Exp/Cntr=0.3,0.1

Type RM Length L Ch R = 1 ,8205.5  ,156.5,159.5,162.5
XS GIS Cut Line= 4
     1833572.643      162289.206     1833358.635      162185.098
       1833097.2      162084.923     1832811.477      161961.213
#Sta/Elev= 30
     1.3 2054.87    12.5 2049.43      35 2036.28    91.3 1998.64   113.8 1984.73
   259.2  1900.3   270.4 1896.91   324.2 1885.45   414.2 1882.84   421.7 1882.66
   429.2 1883.17   434.6 1884.37   443.3 1888.86     465 1904.87   505.1 1931.43
   530.2 1951.49   541.2  1957.1   552.2 1959.86   563.3 1966.12   585.3 1990.26
   589.9 1993.74   596.3 1997.76   640.4 2019.65   689.9 2049.42   702.4 2055.95
     713 2059.37   728.6 2060.93   755.6 2061.62   805.3 2061.17   829.3 2062.09
#Mann= 3 , 0 , 0
       0      .1       0   414.2    .045       0   429.2      .1       0
Bank Sta=414.2,429.2
XS Rating Curve= 0 ,0
Exp/Cntr=0.3,0.1

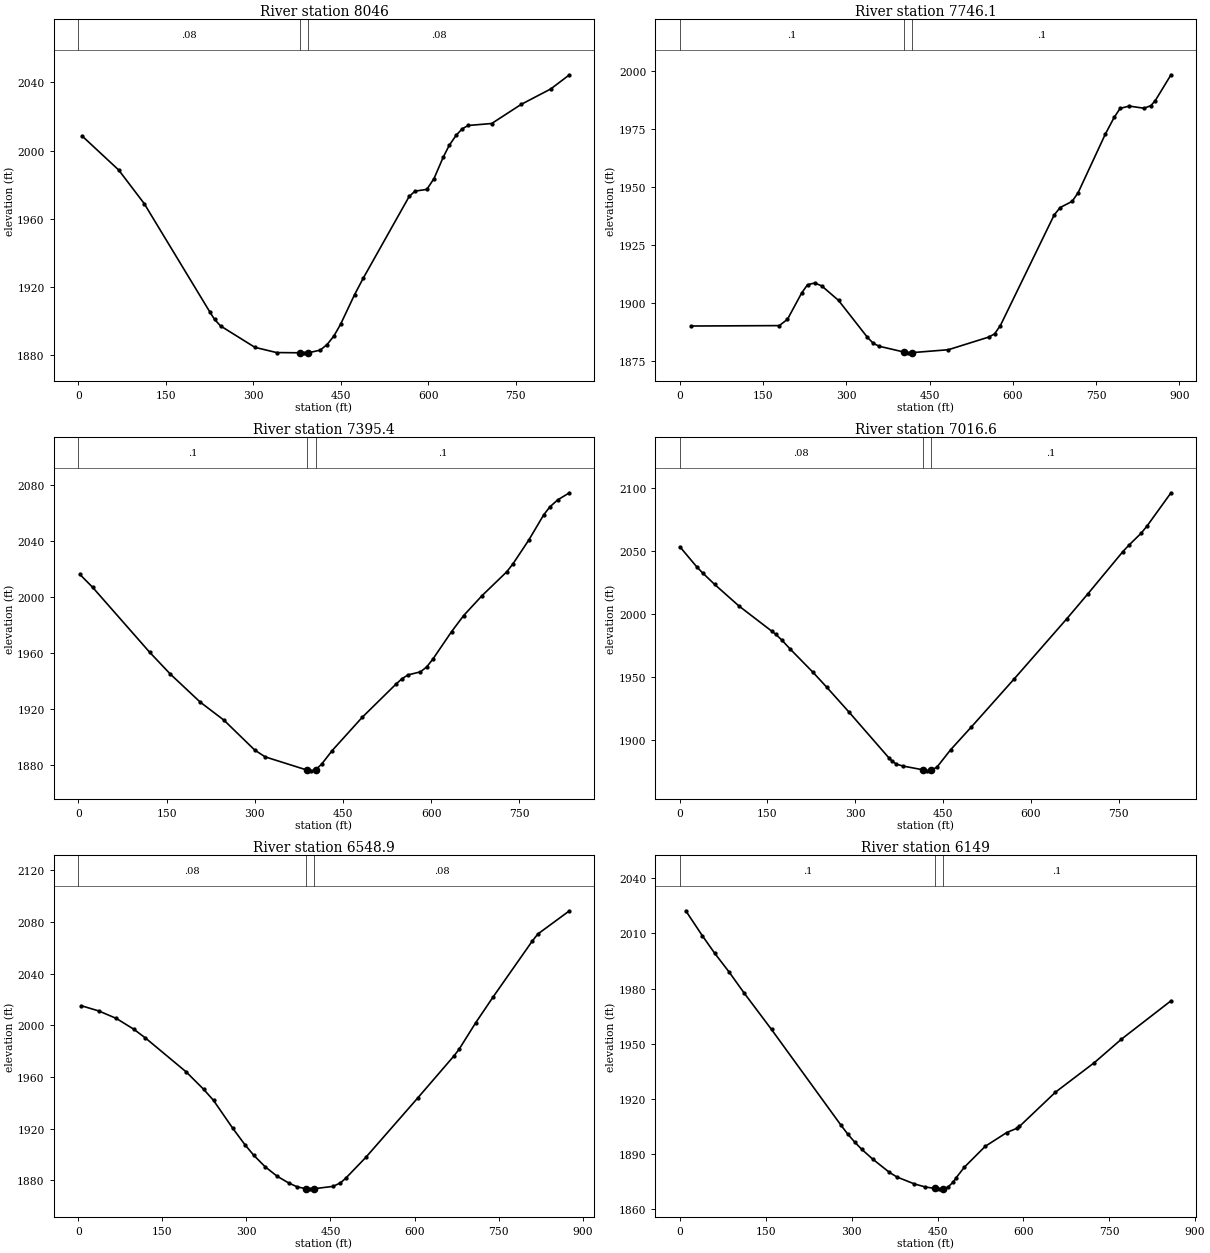
Type RM Length L Ch R = 1 ,8046    ,316.5,300,286.6
XS GIS Cut Line= 4
     1833615.182      162141.119     1833346.418       162031.17
     1833163.169      161928.551     1832821.106      161928.551
#Sta/Elev= 30
     6.5 2008.51    69.1 1988.61   112.8 1968.96   225.8 1905.21   233.6    1901
   243.9 1897.18   302.9 1884.62     340 1881.57   379.4 1881.44   386.9 1881.41
   394.4 1881.43     415 1883.01   426.6 1886.28   438.2 1891.19   449.8 1898.16
   473.8 1915.51   488.6 1925.14   567.5 1973.11   577.6 1976.23   597.8 1977.24
   610.1 1983.59     626 1996.19   636.1 2002.99   648.4 2009.12   658.5 2012.73
   668.6 2014.71   709.1 2015.87   759.7 2027.09   810.3 2036.11   842.5 2044.44
#Mann= 3 , 0 , 0
       0     .08       0   379.4    .045       0   394.4     .08       0
Bank Sta=379.4,394.4
XS Rating Curve= 0 ,0
Exp/Cntr=0.3,0.1

Type RM Length L Ch R = 1 ,7746.1  ,361,350.7,340.3
XS GIS Cut Line= 4
     1833800.874      161845.478     1833582.996        161716.6
     1833258.459      161796.612     1832979.921      161901.674
#Sta/Elev= 30
    19.7  1890.2   179.1 1890.38   193.8  1893.1   219.5 1904.47   229.9 1907.97
     243 1908.72   255.6 1907.45   285.8 1901.23   337.9 1885.33   348.3  1882.8
   358.7 1881.52   403.3 1879.02   410.8 1878.66   418.3 1878.75   483.7    1880
   556.6 1885.45   567.1 1886.83   577.5 1890.41   674.4 1937.97   685.2 1941.19
   706.8 1943.84   717.6 1947.58   766.7 1972.82   782.5 1979.97   793.3 1983.86
   809.6 1984.86   836.6 1983.92   848.8 1985.07   856.7 1987.24     885 1998.33
#Mann= 3 , 0 , 0
       0      .1       0   403.3    .045       0   418.3      .1       0
Bank Sta=403.3,418.3
XS Rating Curve= 0 ,0
Exp/Cntr=0.3,0.1

Type RM Length L Ch R = 1 ,7395.4  ,374.2,378.8,383.4
XS GIS Cut Line= 4
     1833493.017      161405.682     1833260.902      161491.198
     1833065.437      161664.673     1832750.384      161751.191
#Sta/Elev= 30
     2.6 2016.09    24.2 2006.89   121.2  1960.5   156.5 1944.84   207.4  1924.8
   247.4 1912.04     300 1890.59   317.8 1885.73   388.5 1876.36     396 1875.76
   403.5 1876.54   413.6 1880.45   431.8 1890.29   482.8    1914   539.9 1937.58
   550.4 1941.55   560.8 1944.32   581.8 1946.48   592.3 1949.92   602.8 1955.47
   634.9 1975.27   655.3 1986.68   686.7 2000.97   728.7 2017.98   739.2 2023.62
   766.1 2040.61   791.6  2058.7   802.1 2064.39   815.4 2069.39   835.4 2074.45
#Mann= 3 , 0 , 0
       0      .1       0   388.5    .045       0   403.5      .1       0
Bank Sta=388.5,403.5
XS Rating Curve= 0 ,0
Exp/Cntr=0.3,0.1

Type RM Length L Ch R = 1 ,7016.6  ,472.2,467.7,463.3
XS GIS Cut Line= 4
     1833346.809      161121.378     1833162.486      161163.228
     1832867.529      161329.939     1832559.827      161377.389
#Sta/Elev= 30
      .6 2053.35    28.9 2037.71    39.3 2032.66      60 2023.46   101.5 2006.34
     158  1986.2   163.8 1984.04   174.1 1979.58     189 1972.14   227.6 1953.86
   251.7  1941.7   289.3 1922.17   358.2 1885.41     363 1883.25   370.4 1880.81
   381.5 1879.32   414.9  1876.4  422.61 1875.52   429.9 1875.96   439.6 1878.52
   462.8 1892.24   497.7 1910.06   571.6 1948.61   661.1 1996.18   697.4 2016.13
   757.1 2049.63   767.4 2054.72   787.8 2063.96   798.1 2069.78   839.2 2096.27
#Mann= 3 , 0 , 0
      .6     .08       0   414.9    .045       0   429.9      .1       0
Bank Sta=414.9,429.9
XS Rating Curve= 0 ,0
Exp/Cntr=0.3,0.1

Type RM Length L Ch R = 1 ,6548.9  ,406,399.9,393.8
XS GIS Cut Line= 4
     1833131.503      160726.802     1832896.849      160782.637
     1832679.394      160960.999     1832472.263      161248.278
#Sta/Elev= 30
     5.2 2015.13    36.4 2011.09    67.6 2005.33    98.8 1996.98   119.6 1990.21
   192.4 1963.96   223.6 1950.48   241.2 1941.93   275.7 1920.25   297.5 1907.52
     313 1899.51   333.2 1890.65   354.8 1883.27     376 1877.92   390.7 1875.05
   405.8 1873.64   413.3 1873.53   420.8 1873.62   454.5 1875.43   467.6 1878.09
     477 1881.65   512.9 1897.79   605.6 1943.73   670.5 1976.36   679.5 1981.42
   709.3 2002.03   740.3 2021.92   809.9 2064.95   820.1 2070.58   876.6 2088.56
#Mann= 3 , 0 , 0
       0     .08       0   405.8    .045       0   420.8     .08       0
Bank Sta=405.8,420.8
XS Rating Curve= 0 ,0
Exp/Cntr=0.3,0.1

Type RM Length L Ch R = 1 ,6149    ,262.7,252.6,242.5
XS GIS Cut Line= 4
      1832720.93       160489.44     1832506.449      160641.252
     1832342.217       160880.37     1832261.582      161174.609
#Sta/Elev= 30
    10.2 2022.36    39.2 2008.74    60.9 1999.15    85.7 1989.09   111.7 1977.76
     160  1957.7   280.9 1905.75     293  1900.8   305.5  1896.3   317.7 1892.41
   336.9 1887.07     366 1879.87   379.1 1877.36   409.6 1873.58   428.2 1871.96
   445.2 1871.12   452.7 1870.91   460.2 1871.03   467.8 1871.77   477.3 1874.53
   482.4  1876.9   496.9  1882.7   533.3 1894.05   570.9 1901.57   588.3 1903.84
   593.1 1904.89   656.1 1923.57   724.2  1939.7   771.4 1952.46   857.9 1973.33
#Mann= 3 , 0 , 0
       0      .1       0   445.2    .045       0   460.2      .1       0
Bank Sta=445.2,460.2
XS Rating Curve= 0 ,0
Exp/Cntr=0.3,0.1

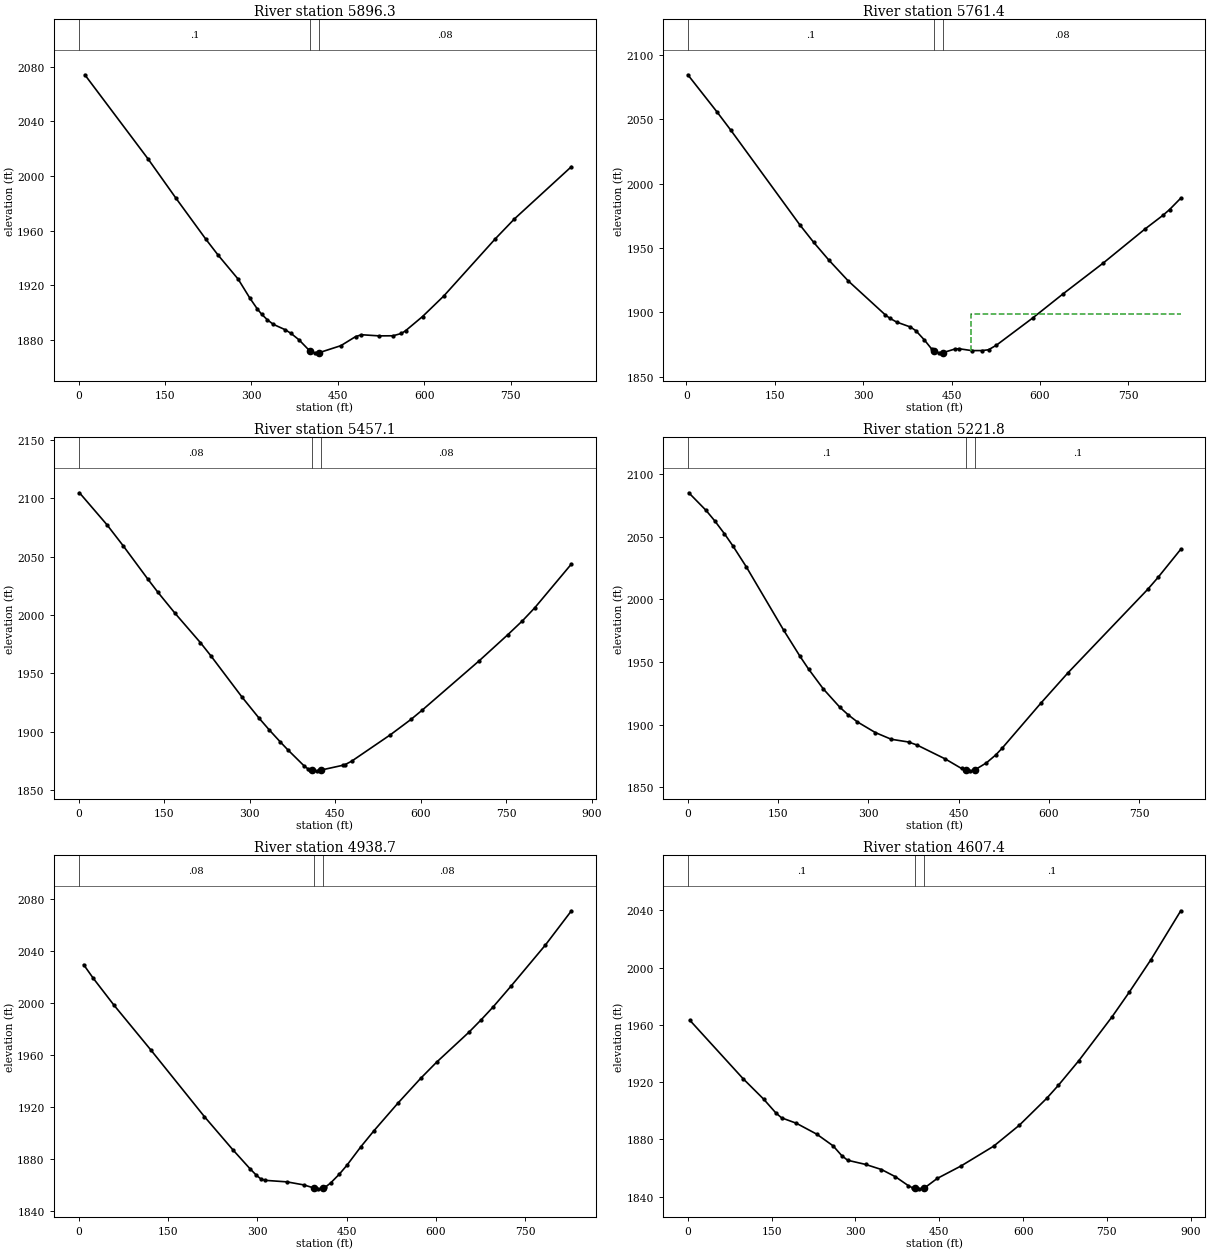
Type RM Length L Ch R = 1 ,5896.3  ,125.5,134.9,144.4
XS GIS Cut Line= 4
     1832402.994       160282.98     1832254.258        160504.1
     1832220.051      160780.194     1832054.822      161043.461
#Sta/Elev= 30
      11 2074.04   120.7 2012.53   169.4 1983.64   221.4  1953.6   242.6 1942.02
   277.1 1924.61   297.5 1910.67   310.2  1902.9   317.8 1898.98     328 1894.79
   338.2 1891.54   358.6 1887.65   368.8 1884.95   382.7 1880.23   399.4 1872.97
   402.1  1872.3   409.6 1870.72   417.1 1870.76   455.3 1875.96   480.9 1882.59
   491.1 1883.96   521.7 1883.12   545.7 1883.19   560.4 1884.89   567.7  1886.9
   597.1 1897.28   633.8 1912.22   723.4 1954.12   756.6 1968.67   855.5 2006.88
#Mann= 3 , 0 , 0
       0      .1       0   402.1    .045       0   417.1     .08       0
Bank Sta=402.1,417.1
XS Rating Curve= 0 ,0
Exp/Cntr=0.3,0.1

Type RM Length L Ch R = 1 ,5761.4  ,298.4,304.3,310.2
XS GIS Cut Line= 4
     1832329.695      160237.168     1832131.176      160576.178
     1832018.173      160744.155      1831920.44      160967.107
#Sta/Elev= 30
     2.6 2084.58    51.9 2055.83    75.4 2041.59   192.6 1967.97     216 1954.44
   241.5 1940.77   274.6 1924.46   337.6 1898.03     345 1895.51   356.7 1892.48
   380.1 1888.64   389.3 1885.79   403.9 1878.53   416.2 1871.54   420.9 1870.01
   428.4 1868.56   435.9 1868.78     455 1871.44   462.2 1871.77   484.1  1870.3
   501.5 1870.31   512.6 1870.95   525.9 1874.47   587.8 1895.72   639.4  1914.5
   707.1 1938.29   777.6  1964.6   808.5 1975.42   819.6 1979.83   838.7 1988.73
#Mann= 3 , 0 , 0
     2.6      .1       0   420.9    .045       0   435.9     .08       0
#XS Ineff= 2 , 0
                          483.02         1899.05
Permanent Ineff=
       F       F
Bank Sta=420.9,435.9
XS Rating Curve= 0 ,0
Exp/Cntr=0.3,0.1

Type RM Length L Ch R = 1 ,5457.1  ,249.4,235.3,220.5
XS GIS Cut Line= 4
     1832268.612      160169.977     1832057.876      160267.709
     1831828.816      160454.012     1831629.092      160725.704
#Sta/Elev= 30
     1.7 2104.72    49.8 2077.42    78.2 2059.46   121.9 2030.64   139.1 2019.66
   169.4 2001.52     214 1976.33   232.3 1965.08   286.9 1929.77   316.9 1911.68
     335 1901.49   354.3 1891.23   367.1  1884.7     396 1870.79   403.2 1868.11
   406.5 1867.29   410.1 1867.04   417.6 1866.63   425.1 1867.25   463.3 1871.34
   467.9 1872.01   479.3 1874.93   547.1 1897.49   583.3 1910.66   602.8 1918.52
   703.2 1960.97   753.3 1983.26   778.9 1995.11   800.4 2006.21   864.8 2043.75
#Mann= 3 , 0 , 0
       0     .08       0   410.1    .045       0   425.1     .08       0
Bank Sta=410.1,425.1
XS Rating Curve= 0 ,0
Exp/Cntr=0.3,0.1

Type RM Length L Ch R = 1 ,5221.8  ,268,283.1,298.3
XS GIS Cut Line= 4
     1832018.173       159980.62     1831734.138      160240.222
     1831682.217      160435.687     1831502.023      160582.286
#Sta/Elev= 30
     1.6 2084.88    30.3 2070.83    44.6 2062.58    60.8 2052.24    74.5  2042.8
    97.2 2025.81   159.1 1975.44   186.5 1954.42   200.6 1944.35   225.2 1928.45
   252.6 1913.87   266.7 1907.74   281.7  1902.2   311.7 1893.65   338.1 1888.32
   366.8 1886.14   381.1 1883.68     428 1872.59   454.9 1865.02   462.3 1863.63
   469.8 1863.14   477.3 1863.96   496.3 1869.52   511.7 1875.78   522.2 1881.09
     587 1917.25     632  1941.4   764.3 2007.85   781.4 2017.32   819.3 2039.85
#Mann= 3 , 0 , 0
       0      .1       0   462.3    .045       0   477.3      .1       0
Bank Sta=462.3,477.3
XS Rating Curve= 0 ,0
Exp/Cntr=0.3,0.1

Type RM Length L Ch R = 1 ,4938.7  ,326.3,331.3,336.2
XS GIS Cut Line= 4
     1831858.576      159869.366     1831683.185      160017.859
     1831419.561      160188.302     1831231.014      160400.535
#Sta/Elev= 30
     8.7 2029.37    24.7 2019.01    59.3 1998.41   121.9 1963.53   211.3 1912.54
   258.9 1887.12   287.7 1872.51   298.8 1867.32   305.9 1864.63   313.4 1863.47
     350 1862.29   378.2 1859.96   394.8 1857.66   402.3 1856.93   409.8 1857.29
   414.3 1858.23   423.1 1861.35   437.8 1868.16   450.5 1874.98   474.3 1889.46
   496.3 1901.77   536.1 1922.78   574.3 1941.87   601.4 1954.46   655.5 1977.44
   676.4 1987.18   696.1 1996.88   725.8 2012.71   783.9 2044.54   827.6 2070.88
#Mann= 3 , 0 , 0
       0     .08       0   394.8    .045       0   409.8     .08       0
Bank Sta=394.8,409.8
XS Rating Curve= 0 ,0
Exp/Cntr=0.3,0.1

Type RM Length L Ch R = 1 ,4607.4  ,494.5,482.4,470.2
XS GIS Cut Line= 4
     1831750.769      159629.651     1831520.348      159775.993
     1831260.746      159864.563     1831066.148      160137.219
#Sta/Elev= 30
     3.6 1963.18    98.8 1922.43   135.5 1908.19   157.5  1898.5   167.8 1895.04
   194.1 1891.29   230.8 1883.64   260.1 1875.45   275.3 1868.73     286 1865.43
   318.1 1862.52   346.6 1858.95   371.5 1853.92   394.4 1847.76   402.4 1846.13
   406.8 1845.84   414.3 1845.47   421.8 1846.11   424.9 1846.48   446.3 1852.72
   489.1 1861.47   547.3 1875.25   593.4 1889.94   642.1  1908.6     663  1917.7
   699.7 1934.95   759.1 1965.54   789.8 1982.68   828.8 2005.51   882.2 2039.64
#Mann= 3 , 0 , 0
       0      .1       0   406.8    .045       0   421.8      .1       0
Bank Sta=406.8,421.8
XS Rating Curve= 0 ,0
Exp/Cntr=0.3,0.1

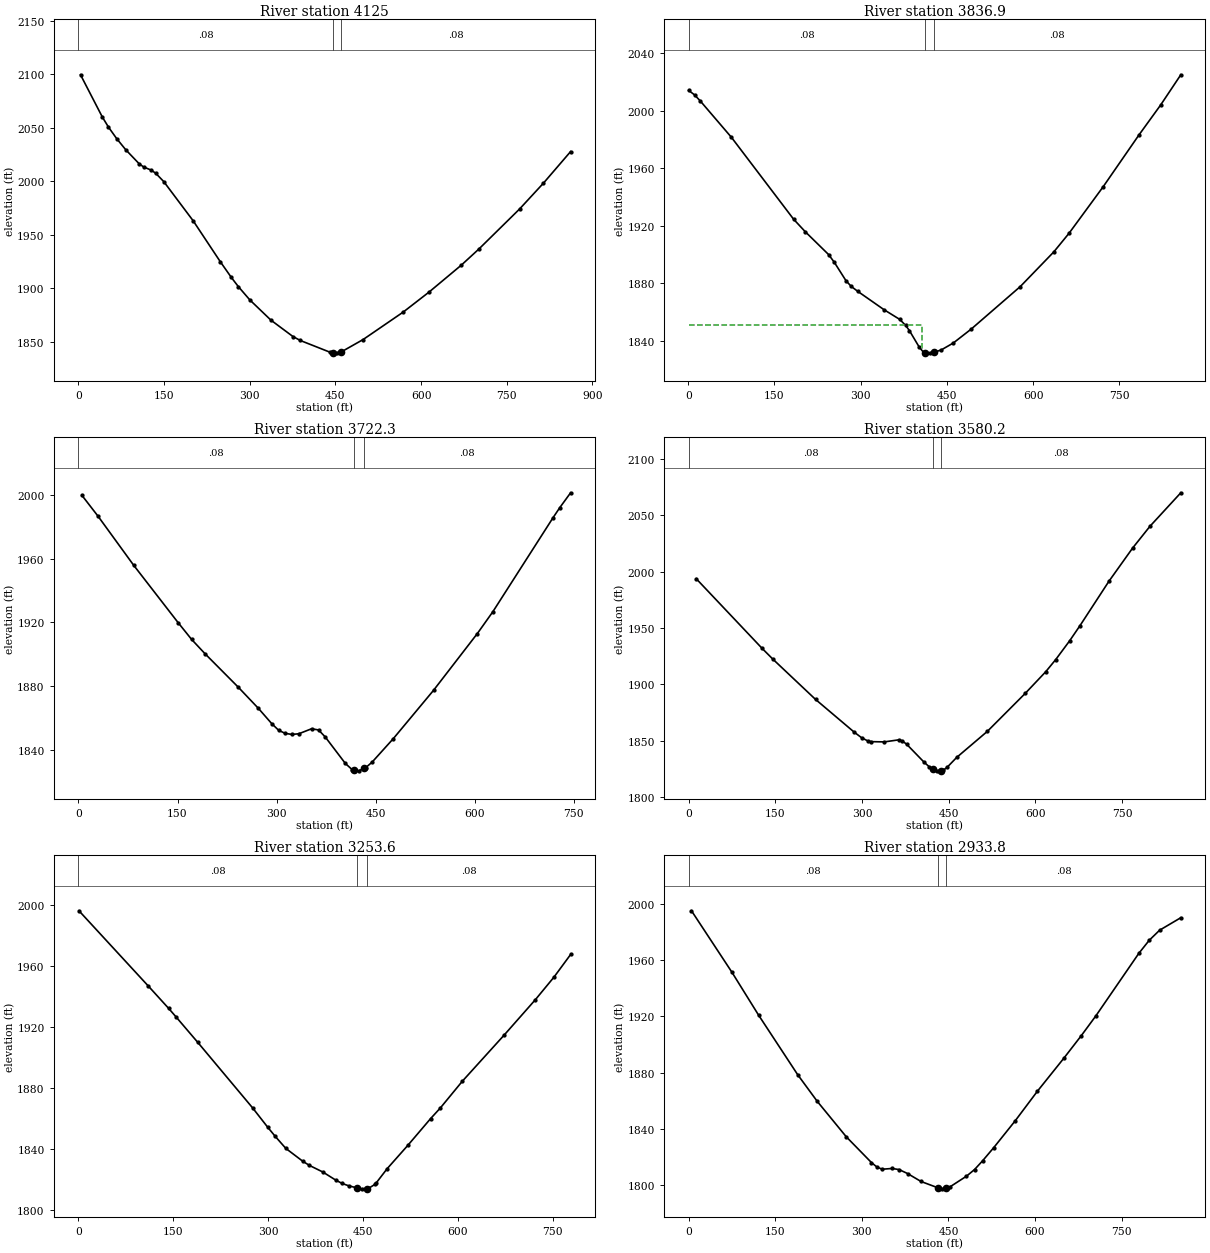
Type RM Length L Ch R = 1 ,4125    ,306.3,288.1,270
XS GIS Cut Line= 4
      1831230.61      159251.412     1831125.259      159541.532
     1830964.494      159745.452     1830832.933      160007.944
#Sta/Elev= 30
     3.6 2099.66    41.8 2060.14    52.5 2050.75    66.8 2040.02    82.6 2029.65
   106.2 2016.46   114.1  2013.4   127.9 2010.35   135.6 2007.37   149.4 1999.71
     201 1962.97   248.3 1924.86   267.8 1910.01   279.9 1901.55   300.1 1889.05
     337 1870.13   375.6 1854.79   388.5 1851.08     440 1840.22   445.4 1839.83
   452.9 1839.52   460.4 1840.44   498.5 1851.96   568.8 1877.68     614 1896.38
   670.6 1921.61   701.1 1936.56   772.4 1974.02   814.2 1998.19   861.9 2027.82
#Mann= 3 , 0 , 0
       0     .08       0   445.4    .045       0   460.4     .08       0
Bank Sta=445.4,460.4
XS Rating Curve= 0 ,0
Exp/Cntr=0.3,0.1

Type RM Length L Ch R = 1 ,3836.9  ,108.3,114.6,120.9
XS GIS Cut Line= 4
     1830740.752      159128.094     1830760.384      159411.065
     1830825.014      159685.479     1830754.816      159968.301
#Sta/Elev= 30
      .7 2014.13    10.9 2011.05      21 2006.76    75.2 1981.45   183.3 1924.52
   203.5 1915.86   244.1 1899.96   254.2  1894.5   274.5  1881.7   283.7 1877.72
   295.1 1874.29   340.6 1861.58     368 1854.81   378.2 1850.66   384.7 1847.09
   401.5 1835.79   409.4 1831.84   412.3 1831.75   419.8 1831.56   427.3 1831.83
   440.6 1833.67   461.3 1838.44   492.5 1848.15   577.7 1877.67   636.1 1901.82
   662.6 1914.78   721.6 1946.94   784.1  1983.1   821.9 2003.98     857 2025.01
#Mann= 3 , 0 , 0
      .7     .08       0   412.3    .045       0   427.3     .08       0
#XS Ineff= 2 , 0
          406.15 1851.02
Permanent Ineff=
       F       F
Bank Sta=412.3,427.3
XS Rating Curve= 0 ,0
Exp/Cntr=0.3,0.1

Type RM Length L Ch R = 1 ,3722.3  ,135.9,142.1,148.3
XS GIS Cut Line= 4
     1830684.204      159139.598     1830689.674      159473.275
     1830676.911      159637.379     1830696.968      159883.535
#Sta/Elev= 30
     5.1 2000.11    29.7 1986.87    83.4 1956.13   151.1 1919.79   171.3 1909.35
   191.6 1900.33   242.2 1879.16   272.5  1865.9   292.7 1856.29   303.3 1852.05
     313 1850.19   323.1 1849.49   333.7 1849.91     353 1853.06   363.6 1852.31
   373.8 1847.86   404.2 1831.21   414.4 1827.36     417  1827.2   424.5 1826.57
     432 1828.06   434.7 1828.46   444.8  1832.1   476.9 1846.89   537.7 1877.26
     604 1912.98   627.5 1926.73   718.8 1986.03   728.9 1992.29   745.3 2001.65
#Mann= 3 , 0 , 0
       0     .08       0     417    .045       0     432     .08       0
Bank Sta=417,432
XS Rating Curve= 0 ,0
Exp/Cntr=0.3,0.1

Type RM Length L Ch R = 1 ,3580.2  ,338.9,326.6,314.4
XS GIS Cut Line= 4
     1830564.402      159104.082     1830594.943       159412.55
     1830488.049      159675.206     1830536.915        159928.7
#Sta/Elev= 30
    13.1 1993.72   126.5 1932.31   145.5 1922.55   219.5 1886.79   286.6  1857.7
   299.3 1852.79   309.5 1850.11   315.2 1849.34   338.5 1849.12     364 1850.97
   369.6    1850   377.3    1847   407.7 1830.95   416.1 1827.17     422 1825.48
   429.5 1823.47     437 1823.64   440.4 1823.95   447.2 1826.58   463.7 1835.32
   516.9 1858.48   582.4 1892.11   617.8 1911.26   635.1 1922.05   659.2 1938.68
   677.1 1952.11   727.2 1991.46   768.4 2021.03   798.4  2040.3   851.6 2069.89
#Mann= 3 , 0 , 0
       0     .08       0     422    .045       0     437     .08       0
Bank Sta=422,437
XS Rating Curve= 0 ,0
Exp/Cntr=0.3,0.1

Type RM Length L Ch R = 1 ,3253.6  ,299.1,319.8,340.5
XS GIS Cut Line= 4
     1830384.208      159067.433     1830210.122      159345.359
     1830260.062      159568.797     1830167.364      159769.885
#Sta/Elev= 30
      .8 1995.97   110.6 1946.62   142.4 1932.15   153.9 1926.68   188.6 1909.84
   275.4 1866.89   299.2 1854.27   311.2 1848.23   327.9 1840.37   354.8 1831.92
   365.2 1829.23   386.5 1824.89   406.7 1819.64     417  1817.4   427.4 1815.87
   440.6 1814.49   448.1 1813.88   455.6  1814.1   458.5 1814.12   468.8  1816.8
   471.2 1817.93   488.1 1827.04   520.7 1842.27   556.9 1859.88     572  1866.7
   607.1 1884.36   672.9 1914.43   722.7 1937.81   751.9 1952.48   778.3 1967.34
#Mann= 3 , 0 , 0
       0     .08       0   440.6    .045       0   455.6     .08       0
Bank Sta=440.6,455.6
XS Rating Curve= 0 ,0
Exp/Cntr=0.3,0.1

Type RM Length L Ch R = 1 ,2933.8  ,340.1,325.2,310.3
XS GIS Cut Line= 4
     1830195.198      159039.501      1830071.47      159295.906
     1829865.004      159495.012     1829707.077      159727.455
#Sta/Elev= 30
     4.9 1994.89    74.8 1951.38   121.5 1920.62     189 1878.52   222.7 1859.72
   273.1 1834.52   316.6 1816.28   326.6 1812.95   335.5 1811.55   352.4 1812.08
   364.6 1811.29   379.2 1808.48   402.5 1802.85   431.5 1798.41     439 1797.63
   446.5 1797.97   453.1 1799.15   481.2  1806.6   495.2 1811.31   509.3 1817.59
   528.6 1826.93   565.5 1845.82   604.2 1866.94   649.9  1890.3   680.1 1906.29
   705.3 1920.31   779.8  1964.7   797.8 1973.96   815.8 1981.11   852.5 1989.97
#Mann= 3 , 0 , 0
       0     .08       0   431.5    .045       0   446.5     .08       0
Bank Sta=431.5,446.5
XS Rating Curve= 0 ,0
Exp/Cntr=0.3,0.1