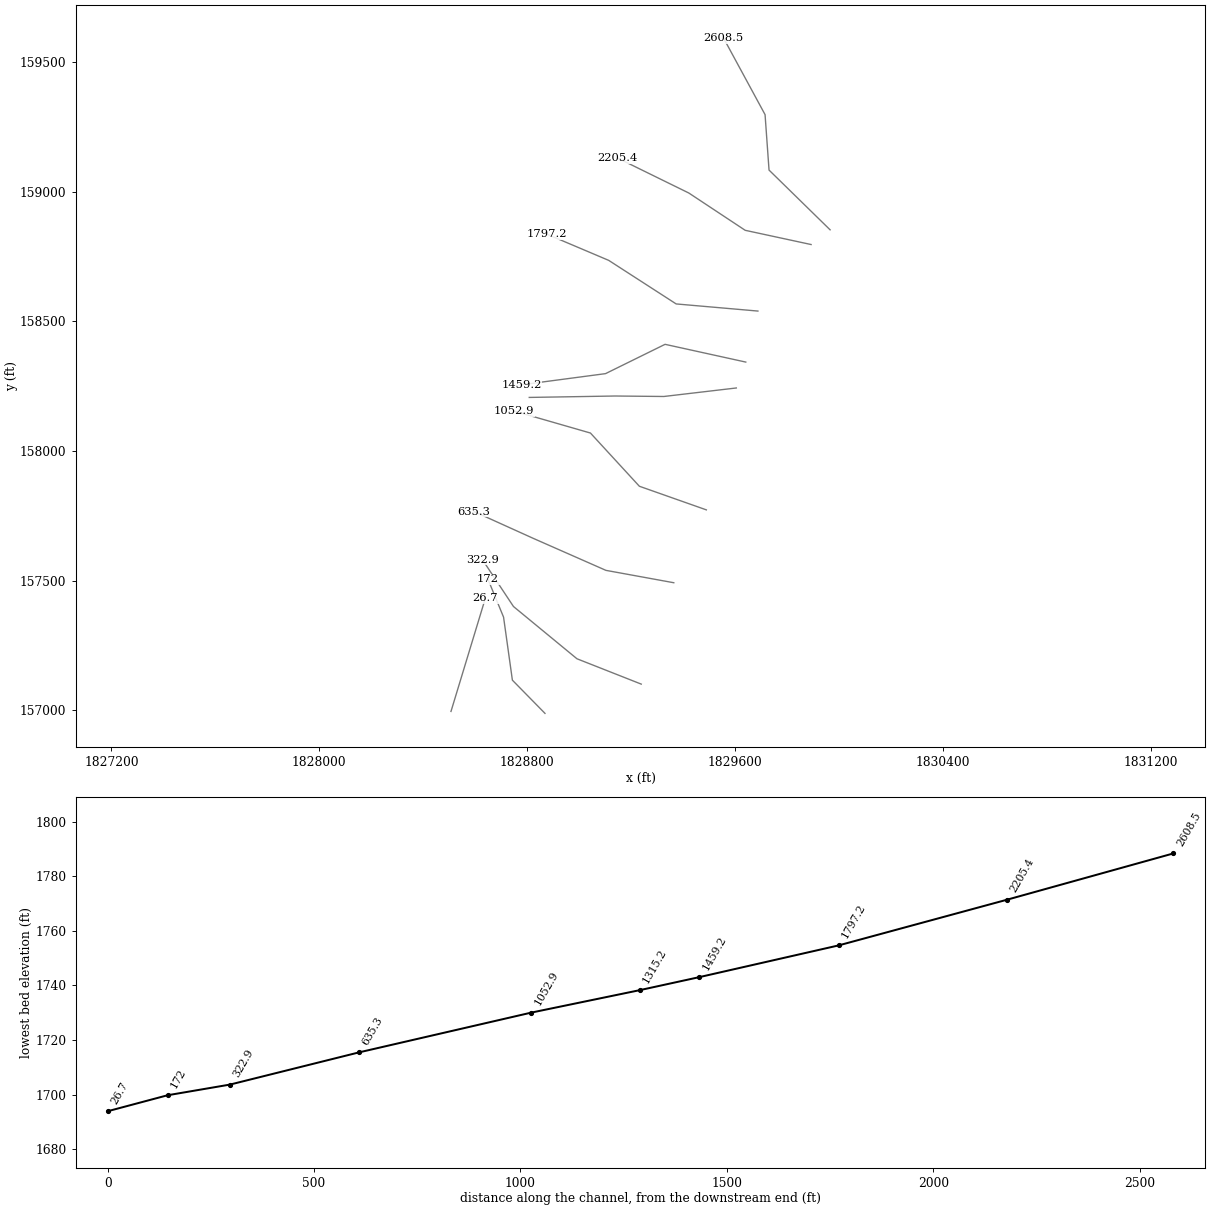
HEC-RAS study Bottom Creek.prj: Bottom Creek

--- Bottom Creek.g01 (geometry) --- (continued)

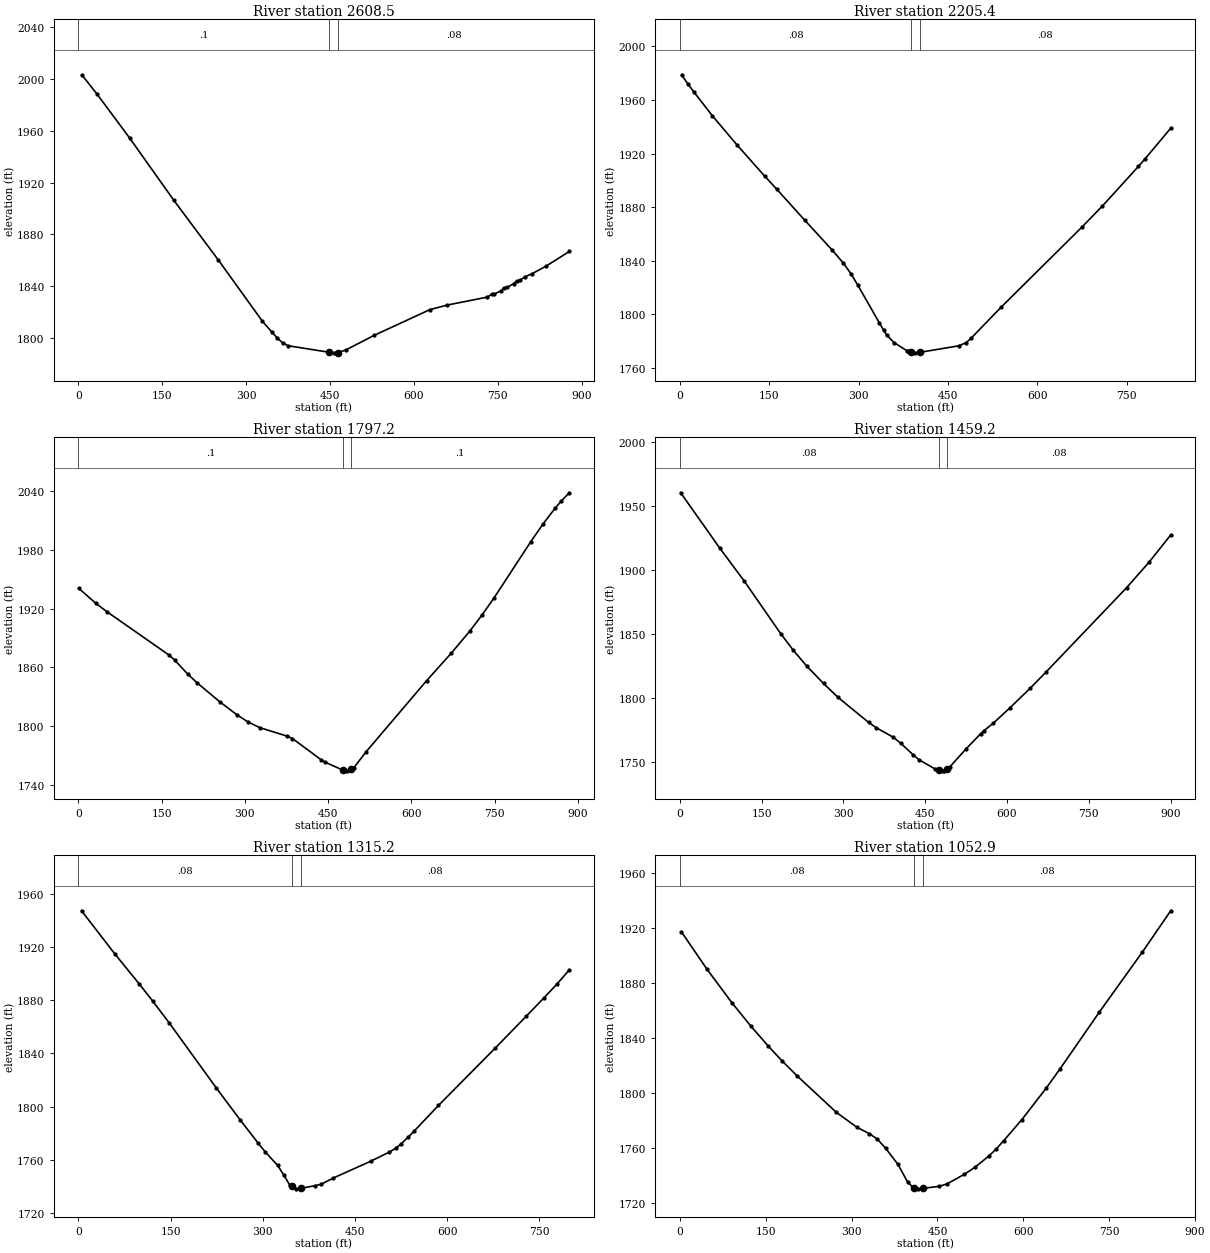
Type RM Length L Ch R = 1 ,2608.5  ,382.9,403.1,423
XS GIS Cut Line= 4
     1829965.603      158852.316     1829730.622      159082.703
     1829715.351      159296.493     1829556.115      159590.707
#Sta/Elev= 30
     6.1  2003.4    33.8 1988.17    91.6  1954.5   170.6 1906.35   250.5    1860
   329.1 1812.77   346.5  1804.2     356 1799.66   365.2 1796.12   374.9 1793.85
     449 1788.76   456.5 1788.35     464 1788.58   477.9 1790.47   528.7 1801.82
   628.8 1821.81     660 1825.32   731.5 1831.46   738.9  1833.6   743.8 1833.82
   755.3 1836.19   761.3 1838.57   766.8 1839.01   778.3 1841.85   783.7 1843.82
   789.8 1844.52   798.6 1847.21   810.5 1849.33   835.8 1855.26     878 1866.73
#Mann= 3 , 0 , 0
       0      .1       0     449    .045       0     464     .08       0
Bank Sta=449,464
XS Rating Curve= 0 ,0
Exp/Cntr=0.3,0.1

Type RM Length L Ch R = 1 ,2205.4  ,407.8,408.2,408.6
XS GIS Cut Line= 4
     1829892.491      158795.614     1829638.921      158850.445
     1829422.154      158994.133     1829148.859      159128.496
#Sta/Elev= 30
       3 1978.87    13.3 1972.21    23.7 1966.04    54.7 1948.26    96.1 1926.49
   142.5 1903.26     163 1893.38   209.9 1870.27   255.4 1848.26   274.2 1838.56
   287.3 1830.42   298.5 1822.12   334.9 1793.79   342.2 1788.25     347  1784.9
   359.7 1778.97   381.6 1772.88   383.4 1772.49   388.1 1772.08   395.6 1771.39
   403.1 1771.78   468.4 1776.64   480.5 1778.97   488.7 1782.16   538.9 1805.26
   674.9 1865.18   709.2 1880.87   769.7 1910.44   781.4 1916.38     824    1939
#Mann= 3 , 0 , 0
       0     .08       0   388.1    .045       0   403.1     .08       0
Bank Sta=388.1,403.1
XS Rating Curve= 0 ,0
Exp/Cntr=0.3,0.1

Type RM Length L Ch R = 1 ,1797.2  ,317.2,338,358.8
XS GIS Cut Line= 4
     1829687.864      158539.066     1829373.288      158566.554
     1829113.686      158734.531     1828874.844      158835.978
#Sta/Elev= 30
      .6 1940.67      31 1925.62    51.3  1916.9     163 1872.75   173.2 1867.67
   197.5 1852.96   213.8 1844.39   255.5 1824.67   286.5 1811.43   305.2  1804.6
   326.7 1798.69   375.5 1790.12   385.6  1787.6   436.8 1766.15   444.1 1763.58
   476.4  1755.4   483.9 1754.64   491.4 1756.26     496 1757.58   517.3 1773.36
   627.5 1846.63   672.2 1874.86   705.1    1897   727.1  1913.4   749.1 1931.13
     815 1988.16     837 2006.17   858.5 2022.09     870 2029.66   884.5 2038.08
#Mann= 3 , 0 , 0
       0      .1       0   476.4    .045       0   491.4      .1       0
Bank Sta=476.4,491.4
XS Rating Curve= 0 ,0
Exp/Cntr=0.3,0.1

Type RM Length L Ch R = 1 ,1459.2  ,153.8,144,134.1
XS GIS Cut Line= 4
     1829641.161       158342.34      1829330.53      158410.793
     1829101.469      158297.789     1828777.677      158254.741
#Sta/Elev= 30
     1.6  1960.2    72.9 1917.22   118.5 1891.05   184.9 1850.24   208.2 1837.15
   232.4 1825.03   263.5 1811.24   290.2 1800.38   346.3 1780.79   360.2 1776.67
   391.7 1769.17   405.3 1764.47   427.8 1755.53   439.1 1751.55   467.2 1744.67
   474.8 1743.39   482.3    1743   484.2 1743.18   489.8 1744.81   495.5 1746.27
   524.1 1759.81   551.9 1772.08   557.8 1774.44   574.4 1780.06     605  1792.1
   642.6 1807.57   671.1    1820   819.3  1886.1   860.1 1905.82   900.1 1927.24
#Mann= 3 , 0 , 0
       0     .08       0   474.8    .045       0   489.8     .08       0
Bank Sta=474.8,489.8
XS Rating Curve= 0 ,0
Exp/Cntr=0.3,0.1

Type RM Length L Ch R = 1 ,1315.2  ,278.7,262.3,245.8
XS GIS Cut Line= 4
     1829604.767      158242.498      1829325.79      158209.677
     1829137.983        158211.5     1828807.952       158206.03
#Sta/Elev= 30
     5.1  1947.2    59.5 1914.66    99.1 1892.17   120.6 1879.53   147.8 1862.93
   224.7 1813.85   263.2 1790.05   292.2 1772.75   303.8  1766.1     324 1755.92
   334.1 1748.73   344.2 1740.79   346.8 1740.12   354.4 1738.24   361.8 1738.65
   384.7 1740.56   394.8 1741.65     415 1746.42   475.7 1759.01   506.1  1765.9
   516.2 1768.73   524.1 1771.62   536.4    1777   546.6 1781.77   585.8 1800.87
   677.9 1843.86   728.7 1867.96   757.4 1881.68   779.2 1892.39   798.8 1902.81
#Mann= 3 , 0 , 0
       0     .08       0   346.8    .045       0   361.8     .08       0
Bank Sta=346.8,361.8
XS Rating Curve= 0 ,0
Exp/Cntr=0.3,0.1

Type RM Length L Ch R = 1 ,1052.9  ,409.3,417.6,425.9
XS GIS Cut Line= 4
     1829489.345      157772.477     1829231.658      157863.545
     1829043.441      158068.729     1828749.813      158153.485
#Sta/Elev= 30
     2.8 1916.99    47.5 1889.75    91.3 1865.23   124.2 1848.34   154.9  1833.7
   178.5 1823.13   204.7 1812.27   273.3 1785.71   309.4 1774.78   330.9  1770.2
   345.2 1766.12   359.5 1759.54     381 1747.86   398.1 1734.82   409.3 1730.38
   416.8 1730.03   424.3 1730.35     453 1731.87   466.7 1733.59   497.1 1740.64
   515.4 1745.67   539.6 1753.83     553 1759.17   565.9 1765.14   597.5  1780.4
   639.6 1803.08   663.4 1816.85   732.7 1858.55   808.1 1902.34   857.4 1932.26
#Mann= 3 , 0 , 0
       0     .08       0   409.3    .045       0   424.3     .08       0
Bank Sta=409.3,424.3
XS Rating Curve= 0 ,0
Exp/Cntr=0.3,0.1

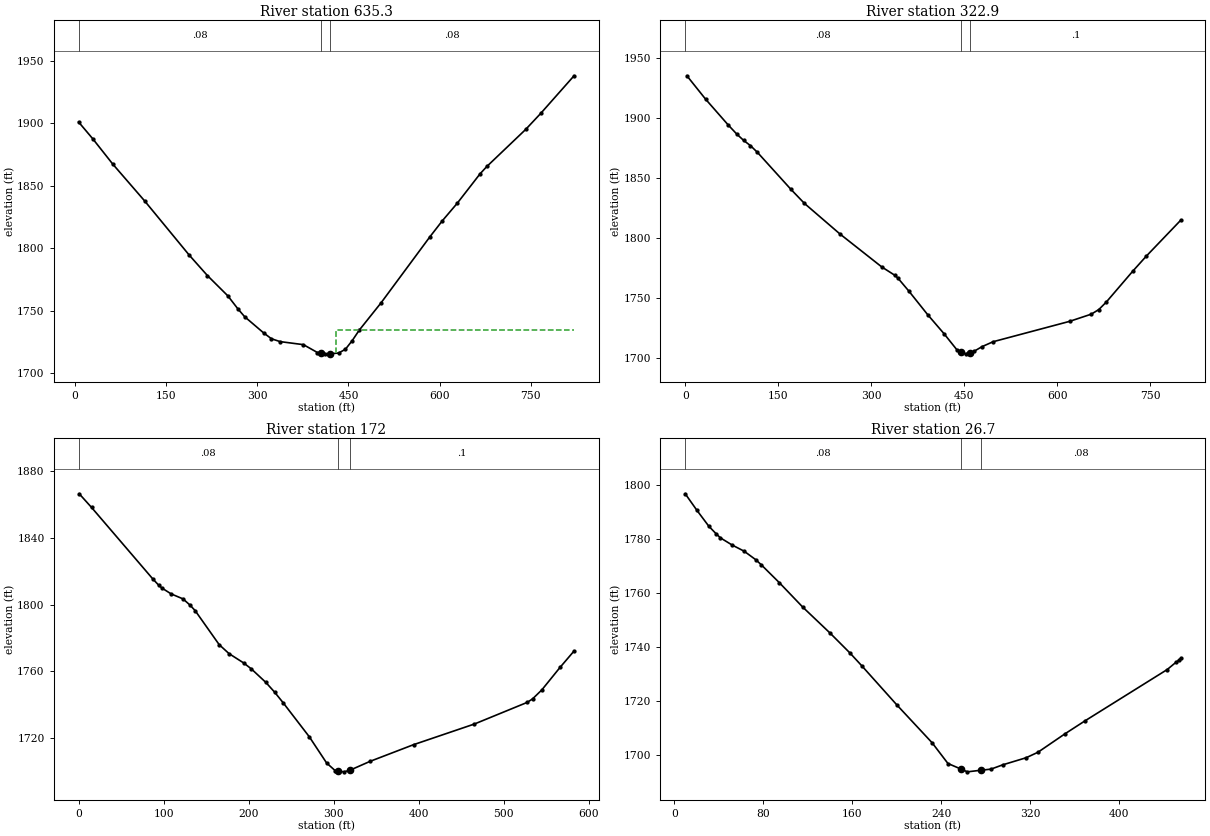
Type RM Length L Ch R = 1 ,635.3   ,317.9,312.4,307
XS GIS Cut Line= 4
     1829364.125      157491.497     1829102.975      157539.206
     1828823.542      157662.528     1828595.658      157765.823
#Sta/Elev= 30
       6 1901.06    29.2 1887.69    62.2 1867.37   114.5 1837.96     188 1794.49
   217.9 1778.13   251.5 1761.88     268 1751.49   279.1 1745.21   310.2 1732.29
   323.3 1727.51   337.5 1725.24   375.8 1722.81   398.9 1716.51   404.3 1715.97
   411.8 1715.45   419.3 1715.48   433.9 1716.12     445 1719.15     456 1725.94
   467.9 1734.54   503.6  1756.3     584  1809.2   604.3 1821.93   628.8 1835.96
   666.5 1859.61   677.6 1865.47   741.5 1895.13   766.5  1908.1   821.1 1938.11
#Mann= 3 , 0 , 0
       6     .08       0   404.3    .045       0   419.3     .08       0
#XS Ineff= 2 , 0
                          428.78         1734.33
Permanent Ineff=
       F       F
Bank Sta=404.3,419.3
XS Rating Curve= 0 ,0
Exp/Cntr=0.3,0.1

Type RM Length L Ch R = 1 ,322.9   ,165.9,150.9,136
XS GIS Cut Line= 4
     1829238.905      157100.567      1828991.52      157198.299
     1828747.189      157399.872     1828628.078      157580.067
#Sta/Elev= 30
     2.7  1935.5    32.7 1916.08    69.4 1894.42    83.4 1886.73    94.3 1881.57
   105.2 1877.23   116.1 1871.82   170.4 1840.81   192.2 1829.08   249.5 1803.57
   316.8 1776.13   338.4    1769   343.2  1766.6   360.6 1755.93   390.9  1736.3
   417.4 1720.35   438.6 1706.62   444.9 1705.18   452.4 1703.66   459.9 1704.77
   465.5 1705.74   478.6 1709.68   496.4 1713.77   619.8 1730.76   654.6 1736.74
   666.8 1740.59   678.9 1746.87   721.4 1772.51   743.3  1785.1   798.7    1815
#Mann= 3 , 0 , 0
       0     .08       0   444.9    .045       0   459.9      .1       0
Bank Sta=444.9,459.9
XS Rating Curve= 0 ,0
Exp/Cntr=0.3,0.1

Type RM Length L Ch R = 1 ,172     ,154,145.3,136.6
XS GIS Cut Line= 4
     1828868.487      156987.738     1828743.073      157115.765
     1828709.106      157358.756     1828649.012      157505.073
#Sta/Elev= 30
      .7 1866.48    15.2 1858.29    87.4 1815.33    94.5 1811.51    98.2 1809.89
   108.7 1806.48   122.8 1803.45   130.8 1799.83     137 1796.46   165.3 1776.03
   176.9 1770.64   194.2 1765.02   203.1  1761.5   220.2 1753.39   230.5 1747.55
   240.7 1741.09   271.3 1720.79   291.7 1705.06   301.7  1700.5   304.7 1700.26
   312.2 1699.76   319.7 1700.86   342.8 1706.05   393.9 1716.04   465.6 1728.45
   527.6  1741.4   533.9  1743.5   544.8 1748.88   566.3 1762.42   582.7  1772.2
#Mann= 3 , 0 , 0
       0     .08       0   304.7    .045       0   319.7      .1       0
Bank Sta=304.7,319.7
XS Rating Curve= 0 ,0
Exp/Cntr=0.3,0.1

Type RM Length L Ch R = 1 ,26.7    ,22.7,26.7,30.7
XS GIS Cut Line= 2
     1828506.768      156995.164     1828638.808      157430.852
#Sta/Elev= 30
     9.9 1796.61    20.5 1790.45    31.1 1784.63    37.7 1781.83    41.6 1780.31
    52.2 1777.65    62.8 1775.42    73.3 1772.26    78.3 1770.37    94.5 1763.78
   115.6 1754.73     140  1745.2   157.9 1737.84   168.5 1733.13   200.6 1718.42
   231.9 1704.62   246.1 1696.98  257.84 1694.92   263.6  1693.9  275.66 1694.49
   284.7 1694.89   295.3 1696.48   316.4 1699.11     327 1701.13   351.5    1708
   369.3 1712.73   443.2 1731.68   451.4 1734.47   453.8 1735.14   455.3 1735.79
#Mann= 3 , 0 , 0
     9.9     .08       0  257.84    .045       0  275.66     .08       0
Bank Sta=257.84,275.66
XS Rating Curve= 0 ,0
Exp/Cntr=0.3,0.1
Stream Node=Bottom Creek    ,Main            , 0 , 0 ,Upstream end
Stream Node=Bottom Creek    ,Main            , 0 , 1 ,Downstream end

Chan Stop Cuts=-1
Use User Specified Reach Order=0